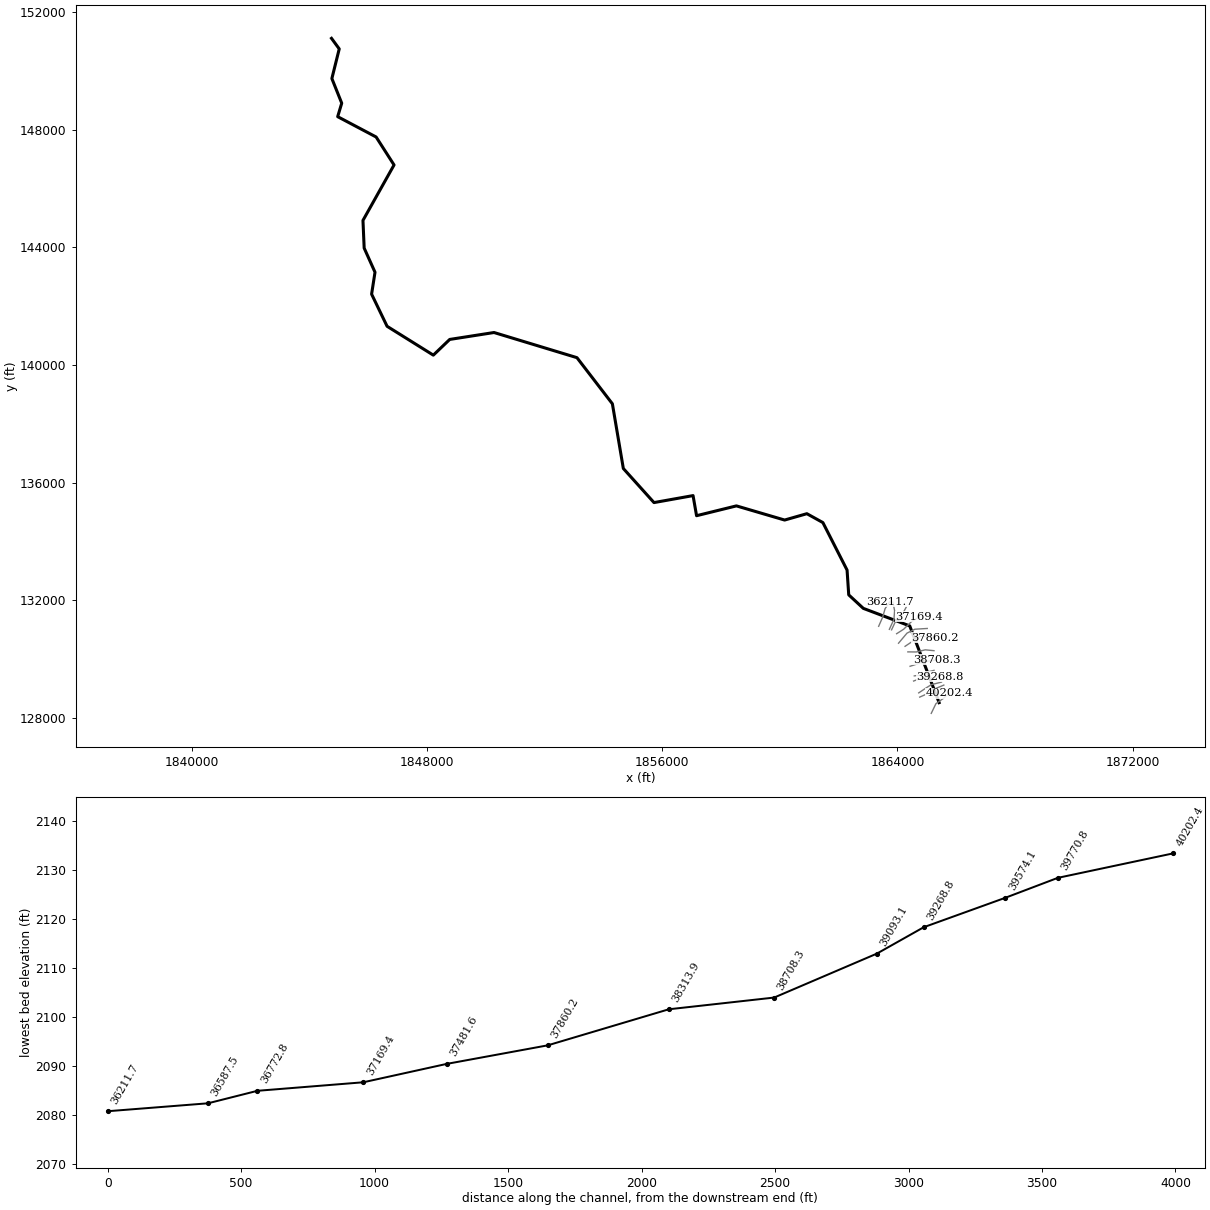
--- Elkhorn Creek.prj (project) ---

Proj Title=Elkhorn Creek
Current Plan=p01
Default Exp/Contr=0,0
English Units
Geom File=g01
Flow File=f01
Plan File=p01
BEGIN DESCRIPTION:
END DESCRIPTION:
DSS Export Rating Curves= 0
DSS Export Rating Curve Sorted= 0
DSS Export Volume Flow Curves= 0
DXF OffsetX= 0
DXF OffsetY= 0
DXF ScaleX= 0
DXF ScaleY= 0

--- Elkhorn Creek.p01 (plan) ---

Plan Title=Floodplain
Program Version=4.00
Geom File=g01
Flow File=f01
K Sum by GR=0
Std Step Tol=0.01
Critical Tol=0.01
Num of Std Step Trials=20
Max Error Tol=0.3
Flow Tol Ratio=0.001
Split Flow NTrial=30
Split Flow Tol=0.02
Split Flow Ratio=0.02
Log Output Level=0
Friction Slope Method=1
Unsteady Friction Slope Method=2
Unsteady Bridges Friction Slope Method=1
Global Log Level=0
CheckData=False
Run HTab=0
Run UNet=0
Run PostProcess=0
UNET Theta=0
UNET Theta Warmup=0
UNET ZTol=0
UNET ZSATol=0
UNET MxIter=0
UNET MaxInSteps=0
UNET DtIC=0
UNET DtMin=0
UNET MaxCRTS=0
UNET WFStab=0
UNET SFStab=0
UNET WFX=0
UNET SFX=0
UNET DSS MLevel=0
UNET DZMax Abort=0
UNET Convert EG Bridges=0
UNET Use Existing IB Tables=0
UNET Froude Limit=0
UNET Froude Power=0
Write IC File=0
Echo Input=False
Echo Output=False
Write Detailed=0

--- Elkhorn Creek.f01 (steady flow) ---

Flow Title=NFF Regression Equation
Program Version=4.00
Number of Profiles=1
Profile Names=P100yr
River Rch & RM=Elkhorn Creek,Main      ,40202.4
629.8654
River Rch & RM=Elkhorn Creek,Main      ,39574.1
636.7805
River Rch & RM=Elkhorn Creek,Main      ,39268.8
725.2917
River Rch & RM=Elkhorn Creek,Main      ,37860.2
744.6941
River Rch & RM=Elkhorn Creek,Main      ,37169.4
825.8767
River Rch & RM=Elkhorn Creek,Main      ,36587.5
887.9992
Boundary for River Rch & Prof#=Elkhorn Creek,Main      ,1
Up Type=0
Dn Type=3
Dn Slope=0.007643

--- Elkhorn Creek.g01 (geometry) ---

Geom Title=USGS 10m DEM
Program Version=4.00

River Reach=Elkhorn Creek   ,Main
Reach XY= 30
     1865419.124      128524.793     1864420.486      131132.911
     1862840.874      131729.782     1862345.033      132188.825
     1862288.322      133031.915     1861465.999      134646.212
     1860921.156       134948.26      1860164.83      134732.443
     1858524.609      135213.814     1857169.396      134879.854
     1857049.925      135563.437     1855721.279      135326.189
     1854678.551      136484.776     1854306.275      138684.325
     1853101.071      140252.907     1850280.628      141107.947
      1848773.29      140872.701     1848215.757      140338.692
     1846643.186      141319.455     1846116.442      142412.391
     1846232.094      143157.959     1845863.551      143978.314
     1845822.687      144919.718     1846879.743      146804.069
     1846269.873      147755.497     1844962.175      148446.283
      1845100.25      148905.074      1844764.86      149742.392
     1845015.439      150750.103     1844752.579      151109.218

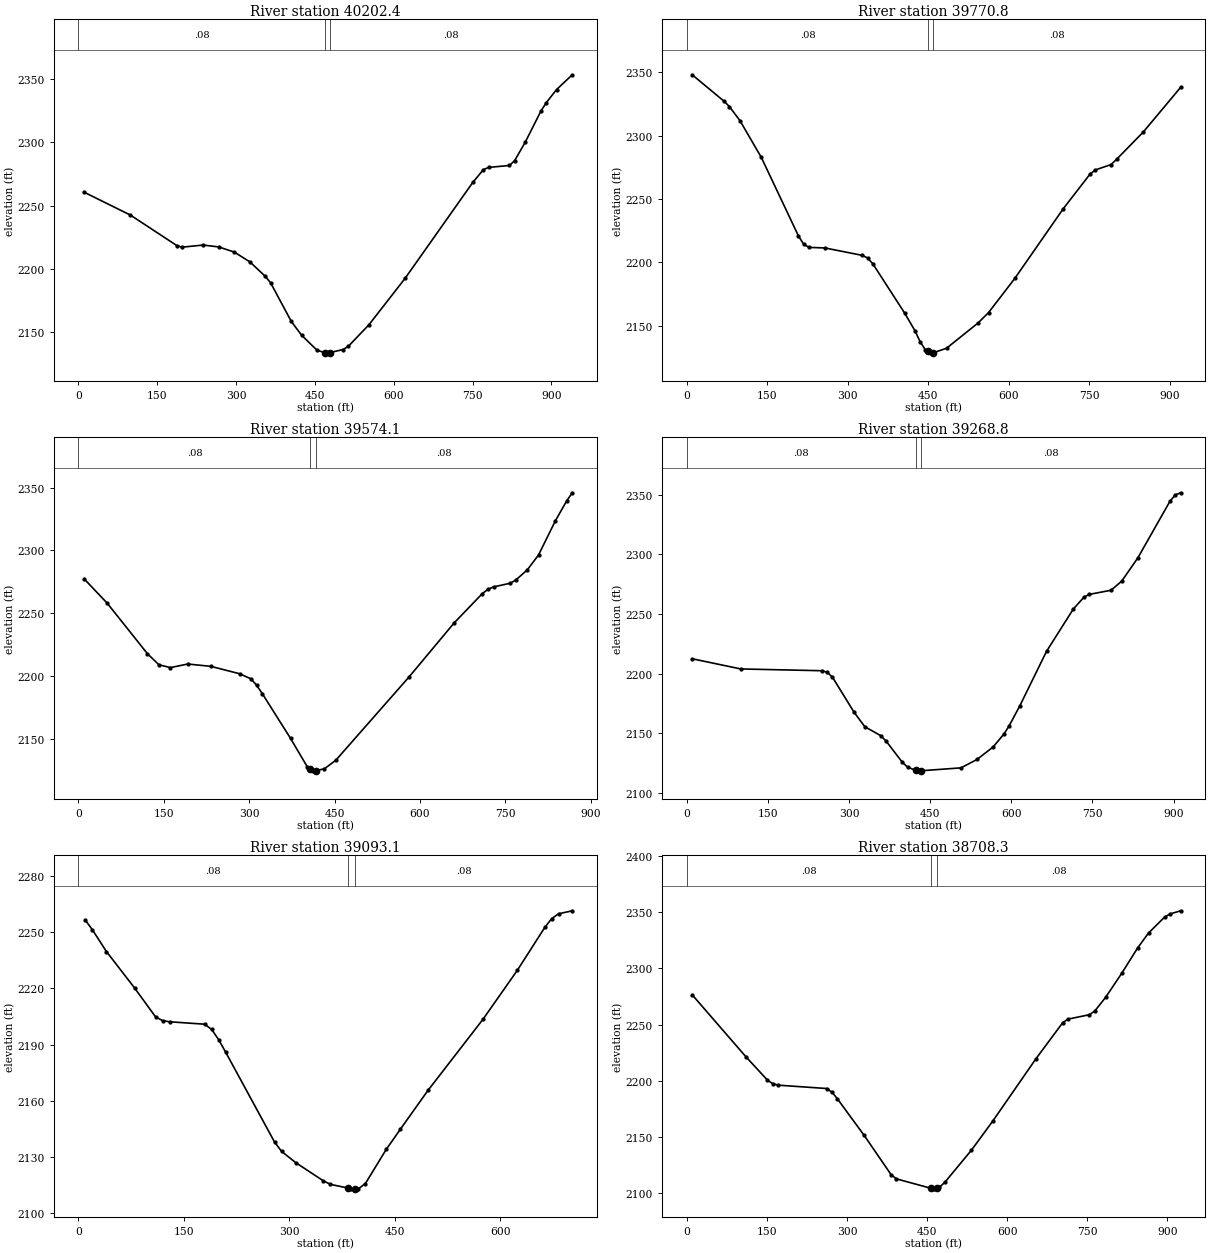
Type RM Length L Ch R = 1 ,40202.4 ,431.7,431.6,431.8
XS GIS Cut Line= 4
     1865151.746      128159.724     1865310.481      128489.306
     1865567.592      128671.399     1865760.206      128844.604
#Sta/Elev= 30
     9.9 2260.78    98.9 2242.48   187.9 2218.17   197.7  2217.1   237.3 2218.74
   266.9 2217.28   296.6 2213.17   326.3 2205.44   355.9 2193.87   365.8 2188.82
   405.2 2158.23   424.9 2147.29   454.4 2135.36   469.1 2133.58   474.1 2133.41
   479.1 2133.65   503.7 2136.02   513.5  2138.5   552.9 2155.64   621.8 2192.45
   750.6 2268.37   770.5 2278.37   780.5 2280.21   820.4 2281.76   830.3 2285.66
   850.2 2300.04   880.1 2324.74   890.1  2331.3     910 2341.87   939.9 2353.56
#Mann= 3 , 0 , 0
       0     .08       0   469.1    .045       0   479.1     .08       0
Bank Sta=469.1,479.1
XS Rating Curve= 0 ,0
Exp/Cntr=0.3,0.1

Type RM Length L Ch R = 1 ,39770.8 ,197.7,196.7,195.5
XS GIS Cut Line= 4
     1864758.558      128712.854     1865085.271       128856.18
     1865285.054      128997.844     1865579.279      129121.346
#Sta/Elev= 30
     9.9 2347.96    69.4 2327.05    79.3 2322.89    99.1 2311.67   138.7 2282.81
   208.1 2220.66     218 2214.06   227.9 2211.68   257.7 2211.21     327 2205.38
   336.9 2203.33   346.9 2198.61   405.8 2159.98   425.3 2145.88   435.1 2137.05
   444.9 2130.69   449.7 2129.58   454.7 2128.42   459.7 2128.53   484.1 2132.03
   542.9 2151.98   562.5 2160.21   611.7 2187.33   701.4 2241.99   751.3 2269.32
   761.2 2272.75   791.1 2277.12   801.1 2281.16     851 2302.77   920.8 2338.11
#Mann= 3 , 0 , 0
       0     .08       0   449.7    .045       0   459.7     .08       0
Bank Sta=449.7,459.7
XS Rating Curve= 0 ,0
Exp/Cntr=0.3,0.1

Type RM Length L Ch R = 1 ,39574.1 ,316.8,305.3,293.8
XS GIS Cut Line= 4
     1864725.662       128856.18     1864969.034      129019.639
     1865154.287      129135.876     1865499.366      129223.054
#Sta/Elev= 30
    10.1 2277.28    50.5 2257.99   121.3 2217.67   141.5 2208.85   161.7 2206.62
   192.1 2209.46   232.5 2207.63   283.1 2201.74   303.1 2197.69   313.1 2192.58
     323 2185.95   372.7 2150.23   402.5 2127.29   407.5 2125.82   412.5 2124.35
   417.5 2124.48   432.3 2126.02   452.2 2132.75   581.1 2199.25   660.2 2242.22
   709.6 2265.52   719.5 2268.98   729.4 2270.92     759 2273.87   768.9 2276.54
   788.7 2284.46   808.5 2296.36   838.1 2323.59   857.9 2339.42   867.8 2345.93
#Mann= 3 , 0 , 0
       0     .08       0   407.5    .045       0   417.5     .08       0
Bank Sta=407.5,417.5
XS Rating Curve= 0 ,0
Exp/Cntr=0.3,0.1

Type RM Length L Ch R = 1 ,39268.8 ,167.1,175.7,184.3
XS GIS Cut Line= 4
     1864551.306      129259.378     1864841.899      129364.718
     1865197.876      129368.351     1865443.004      129406.583
#Sta/Elev= 30
      10 2212.42    99.7 2203.89   249.3  2202.4   259.2  2201.2   269.2 2197.02
   309.1 2167.61   328.9 2155.46   358.5 2147.86   368.4 2143.33   398.1 2125.72
     408 2121.51   422.8 2118.76   427.8 2118.35   432.8 2118.41   506.9 2120.85
   536.5  2127.9   566.2 2138.34     586 2149.07   595.9  2156.1   615.6 2172.86
   665.1 2218.71   714.7 2254.26   734.6 2264.29   744.5 2266.53   784.2 2269.94
     804 2277.55   833.8 2297.07   893.3 2344.67   903.3 2350.05   913.2 2351.79
#Mann= 3 , 0 , 0
       0     .08       0   422.8    .045       0   432.8     .08       0
Bank Sta=422.8,432.8
XS Rating Curve= 0 ,0
Exp/Cntr=0.3,0.1

Type RM Length L Ch R = 1 ,39093.1 ,389,384.8,380.7
XS GIS Cut Line= 4
     1864574.937      129434.592     1864802.282      129464.408
     1865018.446      129565.036     1865245.791      129622.804
#Sta/Elev= 30
      10 2256.32    19.9 2251.22    39.9  2239.6    79.8 2220.21   109.7 2204.75
   119.6 2202.76   129.6 2202.14   179.4 2200.85   189.4 2198.08   199.4 2192.58
   209.4  2185.9     279 2137.88   288.9 2132.97   308.8    2127   348.5 2117.18
   358.4 2115.36   383.3 2113.37   388.3 2112.96   393.3 2112.97   398.2 2112.98
   408.1  2115.8   437.9 2134.11   457.8 2144.78   497.1 2165.51   575.2 2203.41
   624.1 2229.58   663.2 2252.49     673 2257.21   682.8 2259.78   702.3 2261.39
#Mann= 3 , 0 , 0
       0     .08       0   383.3    .045       0   393.3     .08       0
Bank Sta=383.3,393.3
XS Rating Curve= 0 ,0
Exp/Cntr=0.3,0.1

Type RM Length L Ch R = 1 ,38708.3 ,394.2,394.4,394.6
XS GIS Cut Line= 4
     1864431.437      129760.651     1864794.678      129880.521
     1865019.888      129931.375     1865328.157      129977.128
#Sta/Elev= 30
    10.1 2276.53   110.7 2221.43     151 2200.66   161.1 2197.46   171.1 2196.21
   261.7 2193.24   271.8 2190.02   281.8 2184.17   332.2 2151.46   382.5 2116.62
   392.5 2112.85   457.8 2104.41   462.8 2103.99   467.8 2104.67   472.9 2105.37
   482.9 2109.65   533.1 2138.43   573.2 2164.42   653.6 2219.56   703.9 2251.74
   713.9 2254.96   754.1 2258.89   764.2 2262.27   784.3 2274.32   814.5 2295.72
   844.6 2318.49   864.7 2331.54   894.9 2345.76   904.9 2348.51     925 2351.34
#Mann= 3 , 0 , 0
       0     .08       0   457.8    .045       0   467.8     .08       0
Bank Sta=457.8,467.8
XS Rating Curve= 0 ,0
Exp/Cntr=0.3,0.1

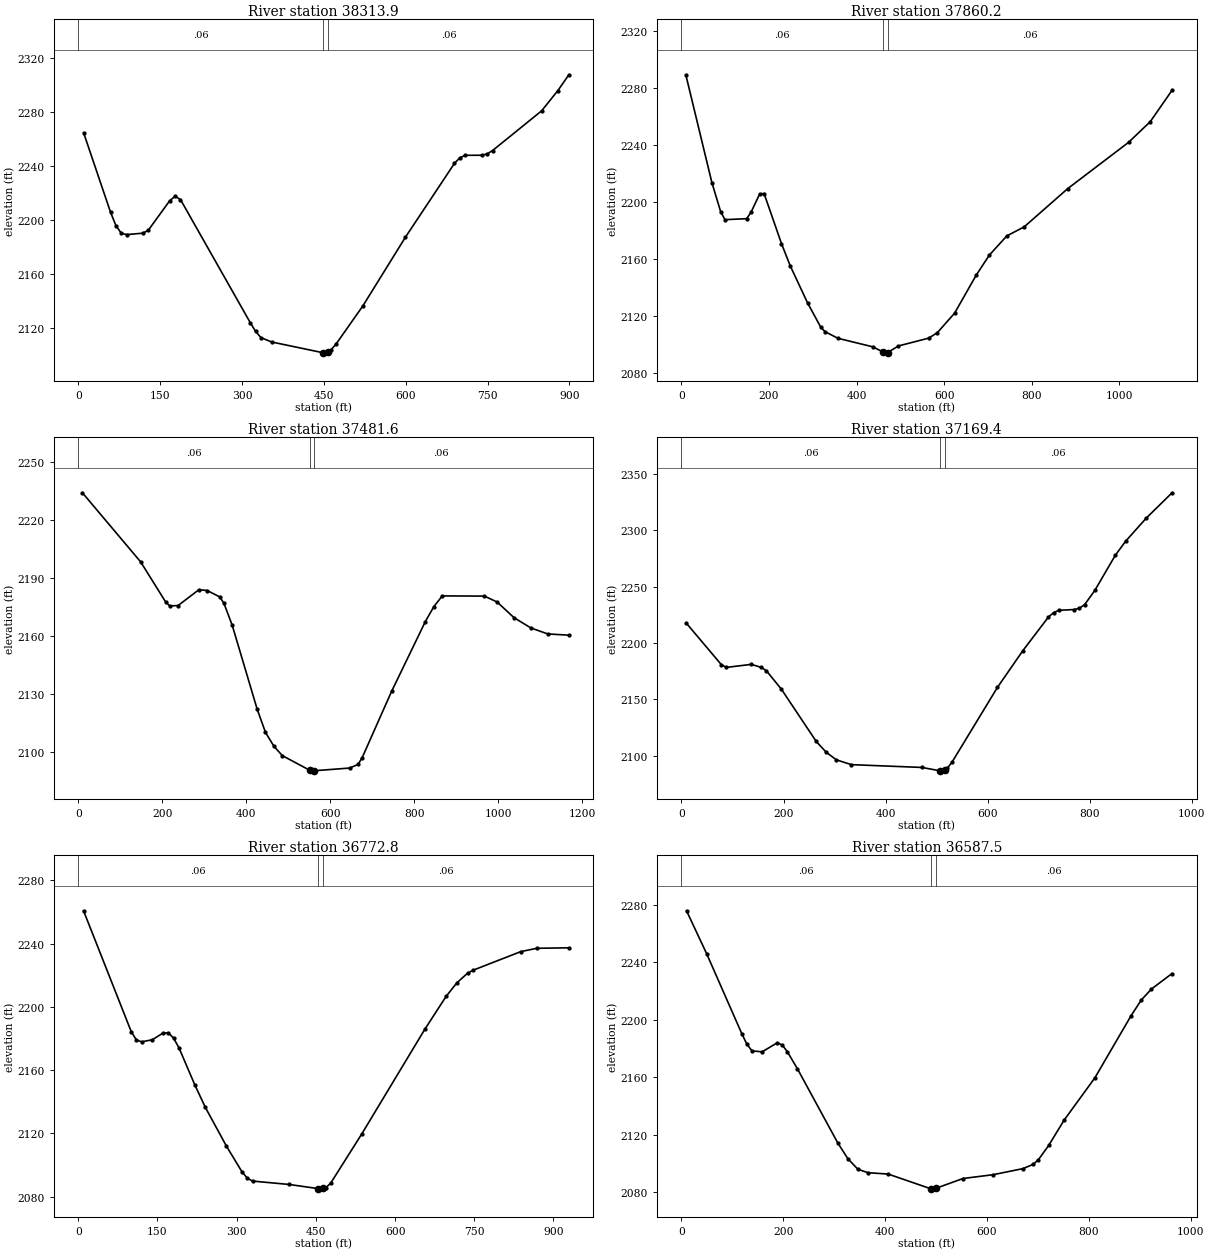
Type RM Length L Ch R = 1 ,38313.9 ,446.4,453.7,461
XS GIS Cut Line= 4
     1864356.304      130250.384     1864642.117      130247.395
     1864947.239      130320.043     1865245.097      130290.984
#Sta/Elev= 30
     9.9 2264.38    59.1  2205.7      69 2195.76    78.8 2190.15    88.7  2189.1
   118.3 2190.17   128.1 2192.21   167.6  2214.2   177.4 2217.48   187.3 2215.02
   315.2 2123.89     325 2117.43   334.8 2112.83   354.4 2109.63   447.5 2101.75
   452.5  2101.6   457.5 2102.57   462.3 2103.51   472.1 2107.98   521.1 2136.13
   599.5 2187.24   689.3 2241.85   699.2 2246.03   709.2 2247.79   739.1 2247.85
   749.1  2248.8   759.1 2251.33   848.9 2280.69   878.8 2295.74   898.8 2307.39
#Mann= 3 , 0 , 0
       0     .06       0   447.5    .045       0   457.5     .06       0
Bank Sta=447.5,457.5
XS Rating Curve= 0 ,0
Exp/Cntr=0.3,0.1

Type RM Length L Ch R = 1 ,37860.2 ,382.6,378.6,368.5
XS GIS Cut Line= 4
     1864260.986      130439.036     1864533.144      130621.533
     1864780.148      130784.992     1865274.156      130734.138
#Sta/Elev= 30
     9.9 2288.99    69.5 2213.42    89.4 2193.21    99.3 2187.51   148.9  2188.2
   158.9 2192.76   178.7 2205.56   188.7  2205.8   228.4 2170.77   248.2 2155.29
     288 2129.22   317.8 2112.39   327.7 2109.11   357.3 2104.43   436.3  2098.5
   460.9  2094.8   465.9 2094.24   470.9 2094.43   495.5 2099.06   564.6 2104.53
   584.4 2108.35   623.9 2122.08   673.5 2148.81   703.3 2162.73   743.1 2176.14
   782.8 2182.48   882.1 2209.24  1021.2 2241.67  1070.8 2256.19  1120.5 2278.14
#Mann= 3 , 0 , 0
       0     .06       0   460.9    .045       0   470.9     .06       0
Bank Sta=460.9,470.9
XS Rating Curve= 0 ,0
Exp/Cntr=0.3,0.1

Type RM Length L Ch R = 1 ,37481.6 ,285.1,312.2,317.2
XS GIS Cut Line= 4
     1864039.136      130545.253     1864326.097      130886.699
     1864594.895      131021.099     1865016.255      131046.526
#Sta/Elev= 30
     9.9 2234.07   148.7 2198.36   208.1  2177.7   218.1 2175.61   237.9 2175.83
   287.4 2184.01   307.3 2183.59     337 2180.28   346.9 2177.05   366.7 2165.71
   426.2  2122.3     446 2110.32   466.1 2103.16   486.1 2098.32   551.2 2090.77
   556.2 2090.45   561.2 2090.48   646.4 2091.89   666.4 2093.73   676.4 2097.26
   746.5 2131.53   826.9 2167.57   847.1 2175.28   867.2 2180.81   967.7  2180.7
   997.8 2177.65    1038 2169.58  1078.2 2164.27  1118.4 2161.16  1168.7 2160.52
#Mann= 3 , 0 , 0
       0     .06       0   551.2    .045       0   561.2     .06       0
Bank Sta=551.2,561.2
XS Rating Curve= 0 ,0
Exp/Cntr=0.3,0.1

Type RM Length L Ch R = 1 ,37169.4 ,394.9,396.6,398.3
XS GIS Cut Line= 4
     1863974.291      130868.334     1864213.492      131021.099
      1864482.29      131282.632      1864741.42        131439.2
#Sta/Elev= 30
     9.8 2217.57    78.3  2180.8    88.1 2178.47     137 2181.16   156.6 2178.43
   166.4 2175.53   195.7 2159.22   264.2 2112.73   283.8 2103.16   303.6 2096.46
   333.2 2092.19   471.3 2089.71   505.8 2086.82   510.8  2086.7   515.8 2087.75
   520.7 2088.78   530.6 2094.65   619.4 2160.79   668.9 2193.18   719.4  2223.2
   729.5 2227.06   739.6  2229.1   769.9  2229.8     780 2230.98   790.1  2234.1
   810.2 2246.72   850.6  2278.1   870.8 2290.52   911.2 2310.99   961.6 2333.38
#Mann= 3 , 0 , 0
       0     .06       0   505.8    .045       0   515.8     .06       0
Bank Sta=505.8,515.8
XS Rating Curve= 0 ,0
Exp/Cntr=0.3,0.1

Type RM Length L Ch R = 1 ,36772.8 ,171.9,185.3,198.7
XS GIS Cut Line= 4
     1863802.271      131000.672     1863917.127      131245.899
     1864163.107      131516.104     1864301.944      131774.075
#Sta/Elev= 30
      10  2260.7   100.3 2184.34   110.3 2178.95   120.4 2177.88   140.4 2179.21
   160.5 2183.44   170.5 2183.56   180.5 2180.24   190.6  2174.2   220.6 2150.78
   240.7 2136.42   280.7 2111.92   310.3  2095.6   320.2 2091.71     330 2089.87
   399.2 2087.73   453.4 2085.15   458.4 2084.96   463.4 2085.21   468.3 2085.45
   478.2 2088.64   537.4 2119.91   656.4 2185.84   696.8 2206.65     717 2215.15
   737.2 2221.21   747.3 2223.08   838.2 2234.91   868.5 2236.99   929.1  2237.3
#Mann= 3 , 0 , 0
       0     .06       0   453.4    .045       0   463.4     .06       0
Bank Sta=453.4,463.4
XS Rating Curve= 0 ,0
Exp/Cntr=0.3,0.1

Type RM Length L Ch R = 1 ,36587.5 ,380.1,375.9,371.6
XS GIS Cut Line= 4
     1863726.748      131017.466     1863883.584      131359.571
     1863904.737      131653.139     1863846.618      131940.099
#Sta/Elev= 30
     9.9 2275.78    49.5 2245.88   118.8 2190.05   128.7 2182.84   138.7 2178.32
   158.5 2177.71   188.2 2184.01   198.1 2182.37     208 2177.74   227.8 2165.86
     307  2114.3   326.8 2103.38   346.6 2095.99   366.4 2093.63   405.8 2092.69
   489.1 2082.53   494.1 2082.41   499.1  2082.7   552.9  2089.6   611.8 2092.23
   670.7 2096.47   690.9 2099.45     701 2102.68   721.2 2112.59   751.4 2130.14
     812 2159.65   882.7 2202.63   902.9 2213.67   923.1 2221.38   963.5 2232.15
#Mann= 3 , 0 , 0
       0     .06       0   489.1    .045       0   499.1     .06       0
Bank Sta=489.1,499.1
XS Rating Curve= 0 ,0
Exp/Cntr=0.3,0.1

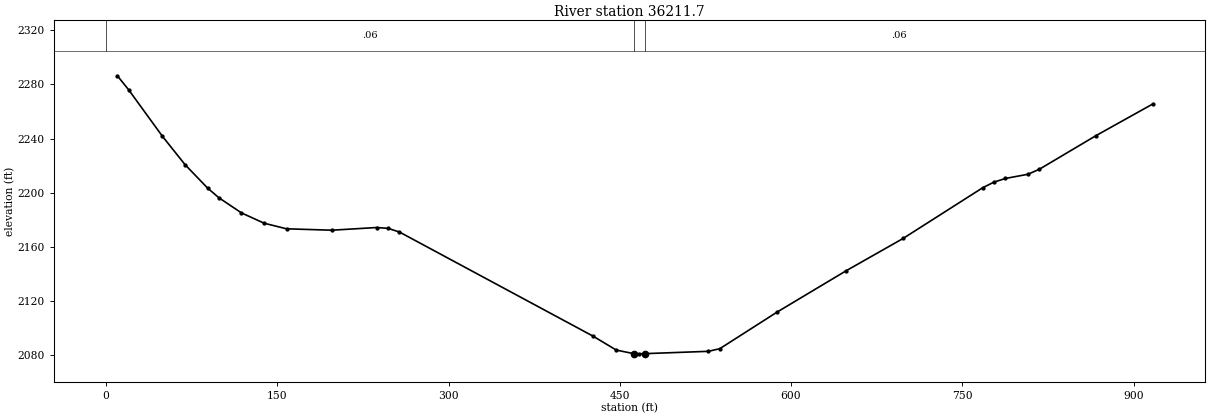
Type RM Length L Ch R = 1 ,36211.7 ,36219.3,36211.7,36203.6
XS GIS Cut Line= 4
     1863362.932      131120.215     1863497.906      131427.929
     1863581.452      131718.522     1863737.182      131949.695
#Sta/Elev= 30
     9.9 2286.44    19.8 2276.04    49.4 2241.64    69.2 2220.69    88.9 2203.42
    98.8 2196.24   118.6 2185.03   138.4 2177.41   158.1 2173.26   197.7 2172.23
   237.2 2174.22   247.1 2173.58     257 2170.87   426.7 2093.81   446.9 2083.57
     462 2080.97     467 2080.79     472 2080.93   527.5 2082.65   537.6  2084.6
     588  2111.8   648.3 2142.25   698.1  2166.1   767.8  2203.6   777.7 2207.78
   787.7 2210.48   807.6 2213.62   817.6 2217.36   867.3 2242.27   917.1  2265.7
#Mann= 3 , 0 , 0
       0     .06       0     462    .045       0     472     .06       0
Bank Sta=462,472
XS Rating Curve= 0 ,0
Exp/Cntr=0.3,0.1

Chan Stop Cuts=-1
Use User Specified Reach Order=0